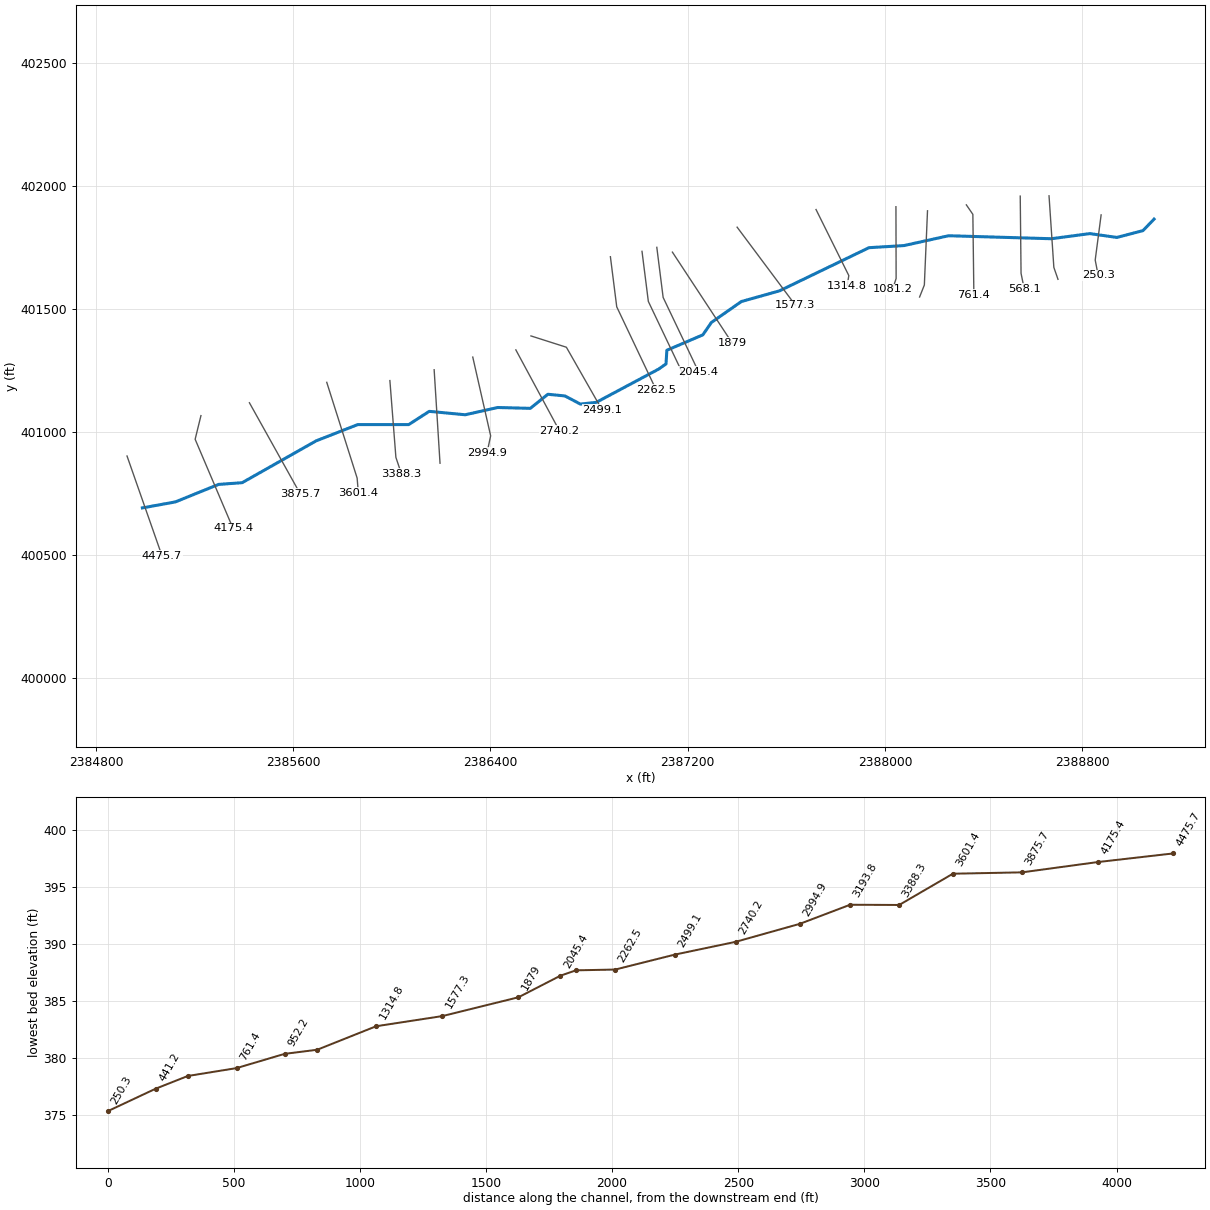
--- GOUGHRUN.prj (project) ---

Proj Title=GOUGHRUN
Current Plan=p01
Default Exp/Contr=0,0
English Units
Geom File=g01
Flow File=f01
Plan File=p01
BEGIN DESCRIPTION:
END DESCRIPTION:
DSS Export Rating Curves= 0
DSS Export Rating Curve Sorted= 0
DSS Export Volume Flow Curves= 0
DXF OffsetX= 0
DXF OffsetY= 0
DXF ScaleX= 0
DXF ScaleY= 0

--- GOUGHRUN.p01 (plan) ---

Plan Title=Floodplain
Program Version=4.00
Geom File=g01
Flow File=f01
K Sum by GR=0
Std Step Tol=0.01
Critical Tol=0.01
Num of Std Step Trials=20
Max Error Tol=0.3
Flow Tol Ratio=0.001
Split Flow NTrial=30
Split Flow Tol=0.02
Split Flow Ratio=0.02
Log Output Level=0
Friction Slope Method=1
Unsteady Friction Slope Method=2
Unsteady Bridges Friction Slope Method=1
Global Log Level=0
CheckData=False
Run HTab=0
Run UNet=0
Run PostProcess=0
UNET Theta=0
UNET Theta Warmup=0
UNET ZTol=0
UNET ZSATol=0
UNET MxIter=0
UNET MaxInSteps=0
UNET DtIC=0
UNET DtMin=0
UNET MaxCRTS=0
UNET WFStab=0
UNET SFStab=0
UNET WFX=0
UNET SFX=0
UNET DSS MLevel=0
UNET DZMax Abort=0
UNET Convert EG Bridges=0
UNET Use Existing IB Tables=0
UNET Froude Limit=0
UNET Froude Power=0
Write IC File=0
Echo Input=False
Echo Output=False
Write Detailed=0

--- GOUGHRUN.f01 (steady flow) ---

Flow Title=NFF Regression Equation
Program Version=4.00
Number of Profiles=1
Profile Names=P100yr
River Rch & RM=GOUGHRUN,Main      ,4475.7
549.4356
River Rch & RM=GOUGHRUN,Main      ,4175.4
604.4286
River Rch & RM=GOUGHRUN,Main      ,2262.5
615.3235
River Rch & RM=GOUGHRUN,Main      ,2045.4
719.6614
River Rch & RM=GOUGHRUN,Main      ,568.1
746.7923
River Rch & RM=GOUGHRUN,Main      ,250.3
748.0877
Boundary for River Rch & Prof#=GOUGHRUN,Main      ,1
Up Type=0
Dn Type=3
Dn Slope=0.007343

--- GOUGHRUN.g01 (geometry) ---

Geom Title=USGS 10m DEM
Program Version=4.10

River Reach=GOUGHRUN        ,Main
Reach XY= 30
     2384988.524      400691.667     2385122.204      400715.973
     2385297.551      400787.153     2385393.037      400794.098
     2385693.385      400964.237     2385861.788      401030.209
     2386068.385      401030.209     2386151.718      401084.028
     2386297.551      401070.139     2386429.496      401099.653
      2386561.44      401096.181     2386632.621      401153.473
     2386702.065      401146.528     2386764.565      401113.542
     2386828.801      401120.487     2387082.274      401255.903
     2387111.787      401276.737      2387115.26      401332.292
     2387261.093      401394.792     2387295.815      401445.139
     2387417.343      401530.209     2387571.857      401573.612
     2387934.704      401748.959     2388077.065      401757.639
     2388257.621       401797.57     2388674.287      401785.417
     2388830.537       401806.25     2388939.912      401790.626
     2389045.815      401818.403     2389090.782      401865.076

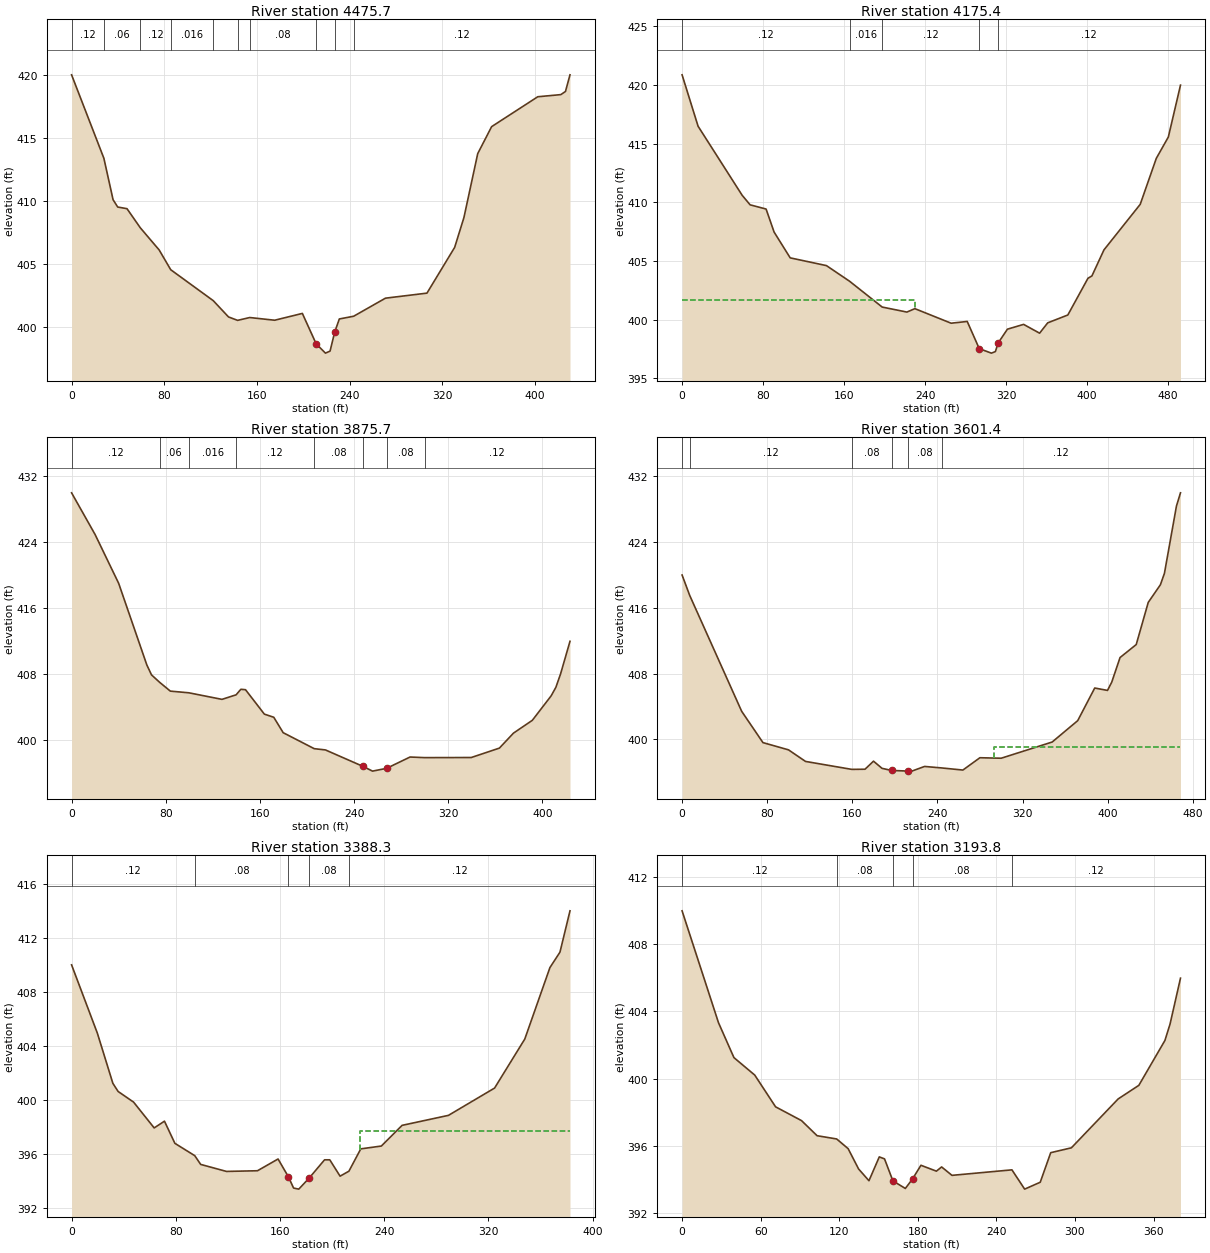
Type RM Length L Ch R = 1 ,4475.7  ,298.8,300.3,301.7
XS GIS Cut Line= 2
     2384926.189      400902.612     2385068.114      400496.669
#Sta/Elev= 30
       0     420   27.87413.3769    35.8  410.09    39.8  409.51    47.8  409.38
   59.32407.8604    75.6   406.1   85.52404.5384  122.23 402.082   135.4  400.79
  143.23400.5191  153.68400.7438   175.2  400.53   199.1  401.07     211  398.66
     219  397.92     223  398.08     227  399.59     231  400.63  243.37 400.847
   270.8  402.28   306.6  402.68   330.5  406.31   338.5  408.68   350.4  413.75
   362.4  415.89   402.2  418.26   422.1  418.43   426.1  418.68     430     420
#Mann= 10 ,-1 , 0
       0     .12       0   27.87     .06       0   59.32     .12       0
   85.52    .016       0  122.23     .12       0  143.23     .06       0
  153.68     .08       0     211    .045       0     227     .08       0
  243.37     .12       0
Bank Sta=211,227
XS Rating Curve= 0 ,0
Exp/Cntr=0.3,0.1

Type RM Length L Ch R = 1 ,4175.4  ,297,299.7,302.4
XS GIS Cut Line= 3
     2385225.933      401066.593     2385202.422      400970.582
     2385356.114      400608.311
#Sta/Elev= 30
       0  420.88    15.8   416.5    59.3  410.62    67.2   409.8      83  409.44
    90.9  407.48   106.8  405.28   142.6  404.62  165.41403.2914  197.71401.0855
   222.1  400.66     230  400.95   265.8  399.71   281.7  399.86   293.6  397.54
   305.6  397.16   309.5  397.29   312.3  398.03   321.4   399.2   337.4  399.61
   353.2  398.86   361.2  399.74   381.1  400.41     401  403.54   404.9  403.74
   416.8  405.96   452.6  409.84   468.5  413.76   480.4  415.58   492.4     420
#Mann= 5 ,-1 , 0
       0     .12       0  165.41    .016       0  197.71     .12       0
   293.6    .045       0   312.3     .12       0
#XS Ineff= 2 , 0
          230.36  401.67
Permanent Ineff=
       F       F
Bank Sta=293.6,312.3
XS Rating Curve= 0 ,0
Exp/Cntr=0.3,0.1

Type RM Length L Ch R = 1 ,3875.7  ,278.8,274.3,269.8
XS GIS Cut Line= 2
     2385422.501      401118.924     2385628.485      400748.938
#Sta/Elev= 30
       0     430      20  424.94      40  419.03    63.9  409.15    67.9  407.93
   74.81 407.029    83.9  405.96   99.65405.7556   127.8  404.96  139.82405.5134
   143.8  406.18   147.8  406.13   163.8  403.17   171.8  402.79   179.8  400.92
  206.17398.9827   215.7  398.83   247.7  396.83   255.7  396.26   267.7   396.6
   287.6  397.97  299.91397.8961   339.6  397.91   363.5  399.05   375.5  400.87
   391.5  402.42   407.5  405.39   411.5  406.42   415.5  408.05   423.5     412
#Mann= 8 ,-1 , 0
       0     .12       0   74.81     .06       0   99.65    .016       0
  139.82     .12       0  206.17     .08       0   247.7    .045       0
   267.7     .08       0  299.91     .12       0
Bank Sta=247.7,267.7
XS Rating Curve= 0 ,0
Exp/Cntr=0.3,0.1

Type RM Length L Ch R = 1 ,3601.4  ,218.2,213,207.9
XS GIS Cut Line= 3
     2385736.114      401201.905     2385859.208      400813.095
     2385864.321      400752.743
#Sta/Elev= 30
       0     420    7.17417.5164      56  403.42      76  399.61     100  398.73
     116  397.32  159.45396.3534   171.9  396.37   179.9  397.35   187.9  396.48
   196.9  396.22   211.9  396.15   215.9  396.14   227.9  396.71  243.85396.5291
   263.9  396.27   279.9  397.77   299.9  397.71   347.8  399.68   371.8  402.28
   387.8  406.25   399.8  405.96   403.8  406.97   411.6  409.96   426.8  411.54
   438.1  416.67   449.5  418.81   453.3   420.2   464.6  428.39   468.4     430
#Mann= 6 ,-1 , 0
       0    .016       0    7.17     .12       0  159.45     .08       0
   196.9    .045       0   211.9     .08       0  243.85     .12       0
#XS Ineff= 2 , 0
                          292.82          399.11
Permanent Ineff=
       F       F
Bank Sta=196.9,211.9
XS Rating Curve= 0 ,0
Exp/Cntr=0.3,0.1

Type RM Length L Ch R = 1 ,3388.3  ,194.7,194.5,194.2
XS GIS Cut Line= 3
     2385992.114      401209.063     2386016.479      400896.902
     2386038.582      400831.005
#Sta/Elev= 30
       0     410    19.8  404.94    31.7  401.23    35.7  400.63    47.6  399.84
    63.4  397.93    71.3  398.43    79.3  396.79   94.55395.8761    99.1  395.23
   118.9  394.71   142.7  394.76   158.5  395.63   166.5   394.3   170.4  393.48
   174.4   393.4   182.3  394.21   194.2  395.57   198.2  395.57   206.1  394.36
  212.88394.7263     222  396.38   237.8  396.59   253.7  398.12   289.3  398.86
   324.7  400.88   347.9  404.51   367.2   409.8   374.9  410.94   382.6     414
#Mann= 5 ,-1 , 0
       0     .12       0   94.55     .08       0   166.5    .045       0
   182.3     .08       0  212.88     .12       0
#XS Ineff= 2 , 0
                          221.37          397.69
Permanent Ineff=
       F       F
Bank Sta=166.5,182.3
XS Rating Curve= 0 ,0
Exp/Cntr=0.3,0.1

Type RM Length L Ch R = 1 ,3193.8  ,195.3,198.9,202.5
XS GIS Cut Line= 2
     2386171.575      401253.077      2386195.39      400873.261
#Sta/Elev= 30
       0  409.99    27.8  403.33    39.6  401.25    55.5  400.21    71.4  398.32
    91.2   397.5   103.1   396.6  118.07396.4062   126.8  395.83   134.8  394.62
   142.7  393.92   150.6  395.34   154.6  395.22     161  393.91   170.5  393.46
     176  394.03   182.4  394.84   194.2  394.49   198.2  394.74   206.1  394.24
  251.88394.5674   261.6  393.42   273.5  393.83   281.5  395.59   297.3  395.88
     333  398.79   348.8   399.6   368.7  402.27   372.6  403.24   380.6  405.98
#Mann= 5 ,-1 , 0
       0     .12       0  118.07     .08       0     161    .045       0
     176     .08       0  251.88     .12       0
Bank Sta=161,176
XS Rating Curve= 0 ,0
Exp/Cntr=0.3,0.1

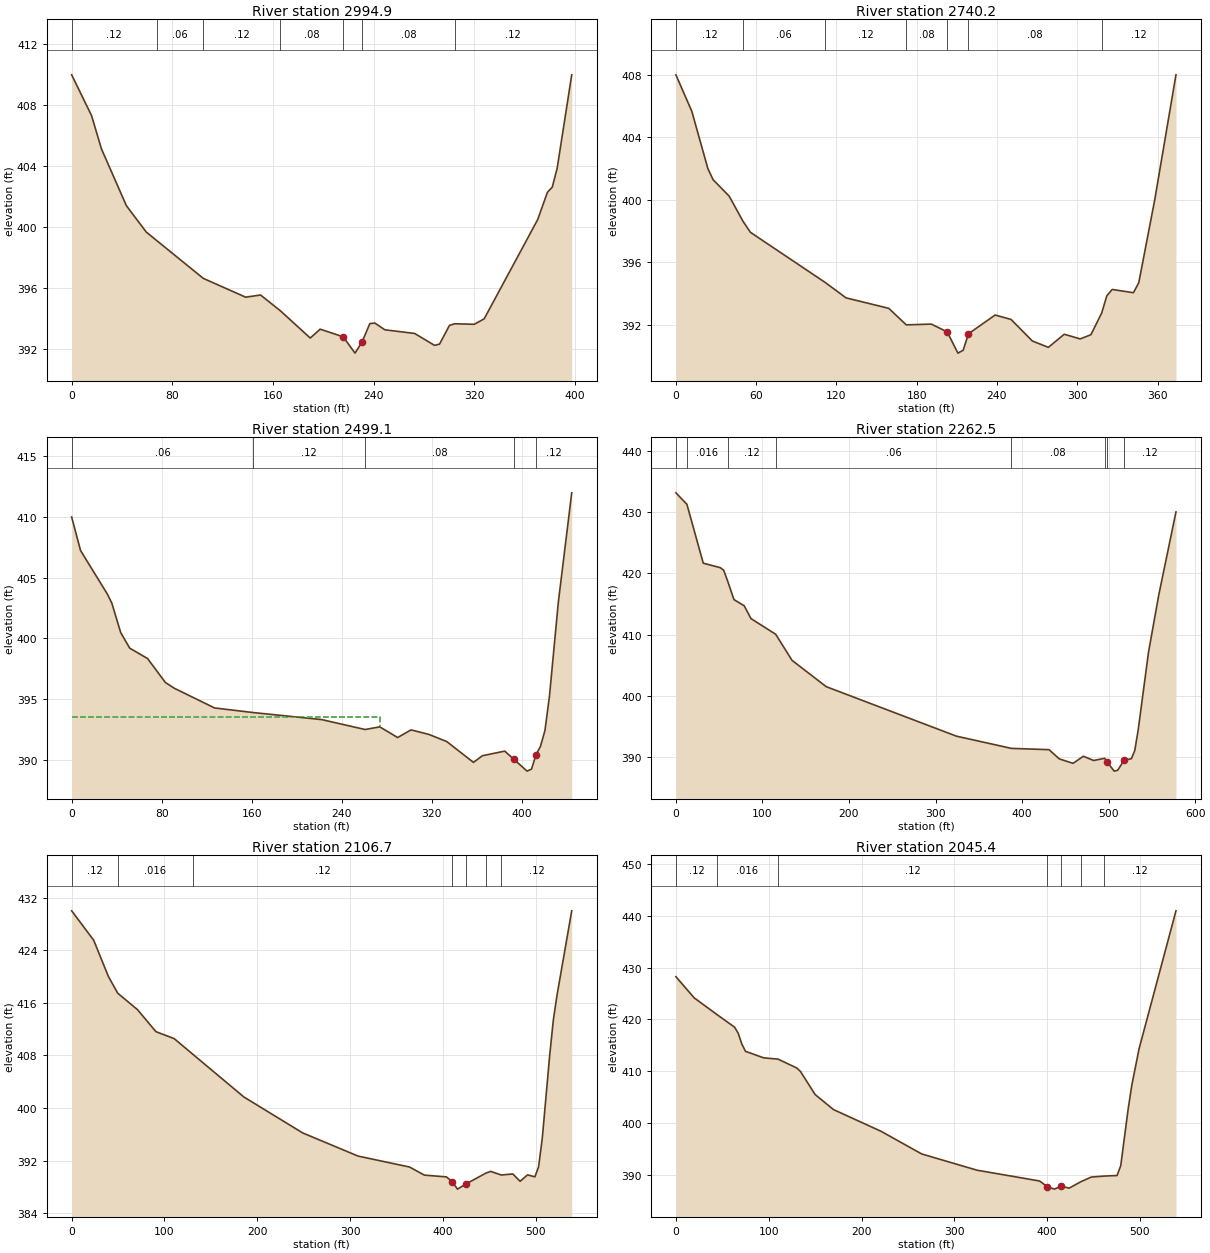
Type RM Length L Ch R = 1 ,2994.9  ,247.4,254.8,261.8
XS GIS Cut Line= 3
     2386328.187      401304.465     2386400.671      400984.537
     2386386.144      400916.537
#Sta/Elev= 30
       0     410    15.8  407.33    23.7  405.14    43.5  401.42    59.3  399.69
   67.66399.1299   104.7396.6505   138.3  395.42   150.2  395.56  165.86394.5333
   189.7  392.74   197.6  393.32   215.9  392.82   225.3  391.75   230.9  392.48
   237.1  393.69   241.1  393.72     249  393.28   272.7  393.04   288.5  392.26
   292.5  392.34   300.4  393.57  304.64393.6751   320.1  393.64     328     394
   370.5   400.5   378.3   402.3   382.1  402.63     386  403.86   397.6     410
#Mann= 7 ,-1 , 0
       0     .12       0   67.66     .06       0   104.7     .12       0
  165.86     .08       0   215.9    .045       0   230.9     .08       0
  304.64     .12       0
Bank Sta=215.9,230.9
XS Rating Curve= 0 ,0
Exp/Cntr=0.3,0.1

Type RM Length L Ch R = 1 ,2740.2  ,240.5,241.1,241.7
XS GIS Cut Line= 2
     2386502.875      401333.776     2386679.896      401004.537
#Sta/Elev= 30
       0     408    11.9  405.66    23.9  401.99    27.8  401.28    39.8  400.23
   50.07398.6286    55.7  397.91  111.46394.7049   127.2  393.71   159.1  393.04
  172.19391.9805   190.9  392.03   202.8  391.53   210.8  390.17   214.7  390.35
   218.7  391.41   238.6  392.61   250.5  392.33   266.4  390.95   278.4  390.54
   290.3  391.38   302.2  391.08   310.2  391.35  318.27392.7389   322.1  393.84
   326.1  394.25     342  394.04     346  394.68   357.9  399.98   373.8     408
#Mann= 7 ,-1 , 0
       0     .12       0   50.07     .06       0  111.46     .12       0
  172.19     .08       0   202.8    .045       0   218.7     .08       0
  318.27     .12       0
Bank Sta=202.8,218.7
XS Rating Curve= 0 ,0
Exp/Cntr=0.3,0.1

Type RM Length L Ch R = 1 ,2499.1  ,238.3,236.6,234.9
XS GIS Cut Line= 3
     2386564.114      401390.444     2386707.752      401344.537
     2386852.898      401089.321
#Sta/Elev= 30
       0     410     7.9  407.24    31.8  403.64    35.7   402.9    43.6  400.47
    51.6  399.19    67.5  398.33    83.3  396.36    91.3  395.88     127  394.26
  161.32  393.88   222.2   393.3  260.78392.4812   273.8   392.7   289.7  391.82
   301.6  392.45   317.4  392.08   333.3  391.49   357.1  389.77     365  390.32
   384.9   390.7   392.8  390.04   404.7  389.05   408.7  389.22   412.7  390.42
   416.6  391.08   420.6   392.4   424.6  395.22   432.5  402.98   444.4     412
#Mann= 5 ,-1 , 0
       0     .06       0  161.32     .12       0  260.78     .08       0
   392.8    .045       0   412.7     .12       0
#XS Ineff= 2 , 0
           273.6  393.48
Permanent Ineff=
       F       F
Bank Sta=392.8,412.7
XS Rating Curve= 0 ,0
Exp/Cntr=0.3,0.1

Type RM Length L Ch R = 1 ,2262.5  ,156.3,155.8,154.9
XS GIS Cut Line= 3
      2386886.26      401712.337     2386911.959      401508.706
     2387071.513      401171.936
#Sta/Elev= 30
       0  433.11    12.7  431.24    31.6  421.64    51.3  420.91    55.3  420.47
   60.28418.5181    67.1   415.7    78.9   414.7    86.8   412.6   115.3410.0541
   134.2   405.8   173.7  401.51   324.2  393.44  387.71391.4478   431.2  391.24
   443.1  389.73     459  389.01   470.9  390.17   482.8  389.47  495.51389.8366
   498.6  389.18   506.5  387.74   510.5  387.87     518  389.52   526.4  389.76
   530.3  391.11   534.3  394.52   546.2  407.16   558.1  416.51   577.9     430
#Mann= 8 ,-1 , 0
       0     .06       0    12.7    .016       0   60.28     .12       0
   115.3     .06       0  387.71     .08       0  495.51     .12       0
   498.6    .045       0     518     .12       0
Bank Sta=498.6,518
XS Rating Curve= 0 ,0
Exp/Cntr=0.3,0.1

Type RM Length L Ch R = 1 ,2106.7  ,61.2,61.3,61.3
XS GIS Cut Line= 3
     2387014.415      401734.237     2387040.114      401530.606
     2387183.334      401229.317
#Sta/Elev= 30
       0     430    23.7  425.54    39.5  420.04    49.6417.4744      71  414.96
    90.8  411.62   110.5  410.56  130.44 408.197   185.5  401.69   248.9  396.22
   308.5   392.7   364.1  391.03     380   389.8   403.8  389.53     410  388.81
   415.7  387.67     425  388.46  446.34390.1098   451.5  390.37  462.94389.8139
   475.3  389.98   483.2  388.86   491.2  389.84   499.1  389.54   503.1  391.06
   507.1  395.44     515  407.93     519   413.4     523   417.2   538.8     430
#Mann= 7 ,-1 , 0
       0     .12       0    49.6    .016       0  130.44     .12       0
     410    .045       0     425     .12       0  446.34    .016       0
  462.94     .12       0
Bank Sta=410,425
XS Rating Curve= 0 ,0
Exp/Cntr=0.3,0.1

Type RM Length L Ch R = 1 ,2045.4  ,163.2,166.4,169.5
XS GIS Cut Line= 3
     2387074.437      401750.459     2387100.136      401546.828
     2387243.356      401245.539
#Sta/Elev= 30
       0  428.25    19.7  424.16   44.11420.9511    63.2   418.5    67.1  417.34
      71  415.25      75  413.83    94.7  412.56  109.97 412.329   130.2  410.61
   134.2  409.94     150  405.48   169.7  402.58   221.1  398.37   264.8     394
   324.4  390.86   391.9  388.77     400  387.68   407.8   387.2     415  387.77
   423.7  387.39  436.42388.6384   447.5  389.53   461.7389.7253   475.3  389.83
   479.3  391.74   487.2  402.57   491.2  407.27   499.1  414.36   538.8  440.98
#Mann= 7 ,-1 , 0
       0     .12       0   44.11    .016       0  109.97     .12       0
     400    .045       0     415     .12       0  436.42    .016       0
   461.7     .12       0
Bank Sta=400,415
XS Rating Curve= 0 ,0
Exp/Cntr=0.3,0.1

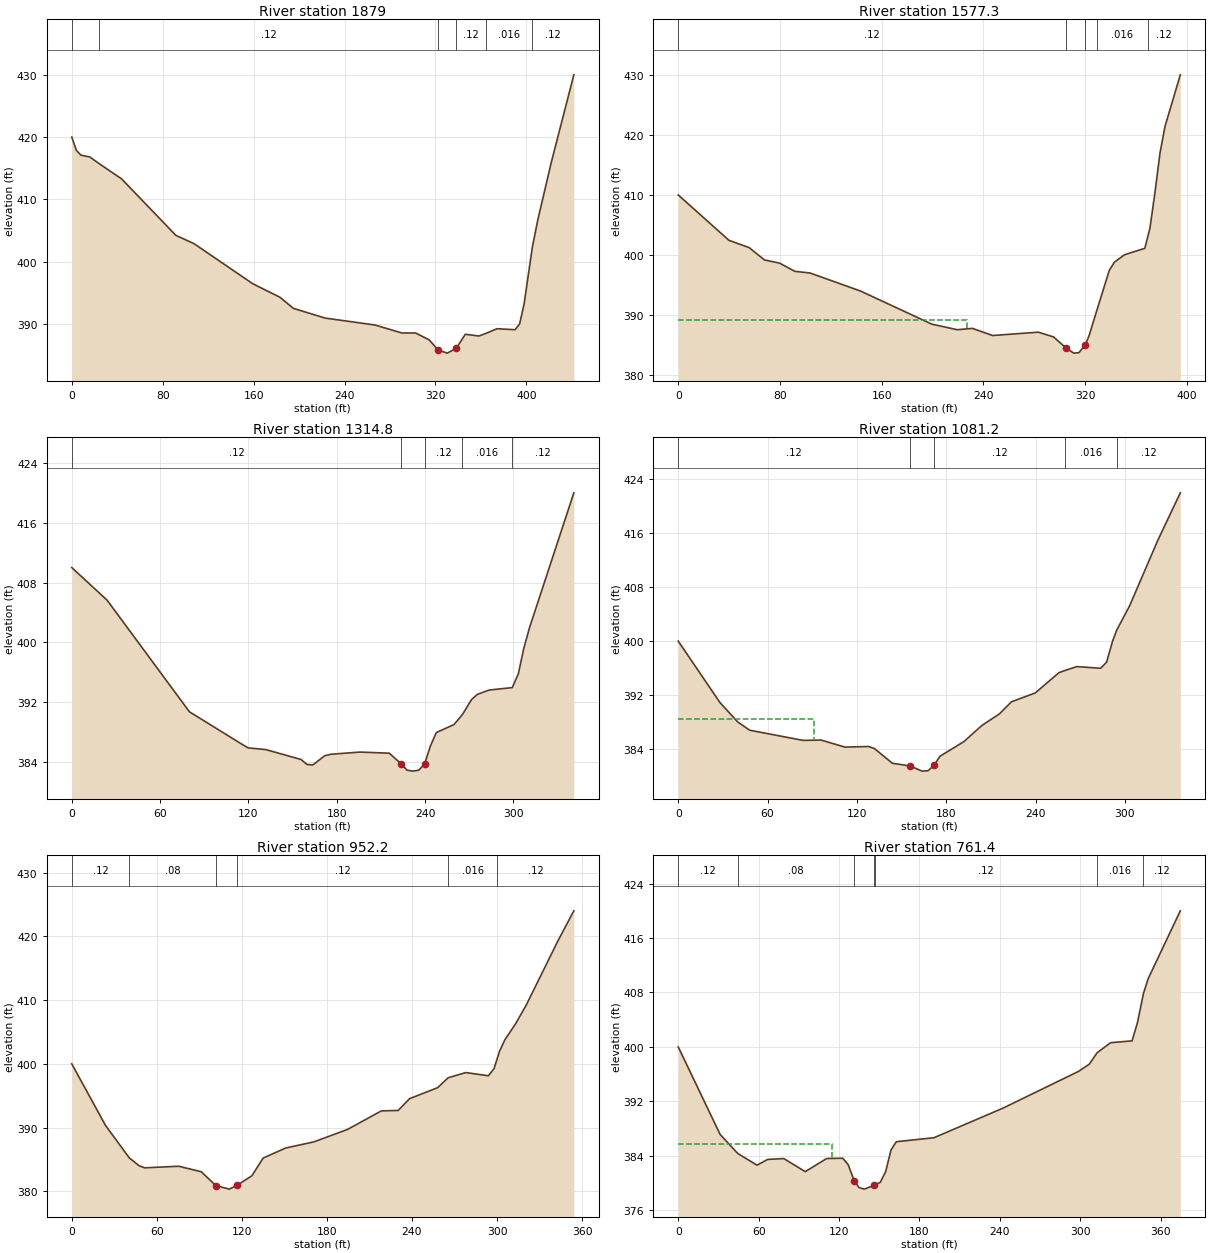
Type RM Length L Ch R = 1 ,1879    ,300.4,301.7,303.1
XS GIS Cut Line= 2
     2387137.713      401730.938     2387380.114      401361.533
#Sta/Elev= 30
       0     420       4   417.9       8   417.1    15.9  416.81   23.76415.7817
    43.8   413.3    91.6  404.22   107.5   402.9   159.2  396.46   183.1  394.29
     195   392.5   222.9  390.94   266.7  389.83   290.6  388.54   302.5  388.55
   314.5  387.44   322.4  385.81   330.4  385.31   338.3  386.08   346.3  388.34
   358.2  388.06  364.28388.4664   374.2  389.23   390.1  389.07   394.1     390
     398  393.18   405.3402.3302     410  406.64   421.9   415.9   441.8     430
#Mann= 6 ,-1 , 0
       0    .016       0   23.76     .12       0   322.4    .045       0
   338.3     .12       0  364.28    .016       0   405.3     .12       0
Bank Sta=322.4,338.3
XS Rating Curve= 0 ,0
Exp/Cntr=0.3,0.1

Type RM Length L Ch R = 1 ,1577.3  ,266.5,262.5,258.3
XS GIS Cut Line= 2
     2387400.114      401832.356     2387636.114      401515.751
#Sta/Elev= 30
       0     410    39.9  402.44    55.8  401.23    67.8  399.18    79.8  398.64
    91.7  397.28   103.7     397   143.6  393.98   199.4  388.49   219.4  387.56
   231.4  387.78   247.3  386.59   283.2  387.15   295.2  386.36   305.1   384.5
   311.1  383.66   315.1  383.73   320.1     385   323.1  386.54  329.03390.6234
     339  397.41     343  398.79     351  400.04     367  401.11  369.51403.2121
     371  404.46   374.9  410.29   378.9  416.95   382.9  421.44   394.9     430
#Mann= 5 ,-1 , 0
       0     .12       0   305.1    .045       0   320.1     .12       0
  329.03    .016       0  369.51     .12       0
#XS Ineff= 2 , 0
          227.47  389.25
Permanent Ineff=
       F       F
Bank Sta=305.1,320.1
XS Rating Curve= 0 ,0
Exp/Cntr=0.3,0.1

Type RM Length L Ch R = 1 ,1314.8  ,244,233.6,223.2
XS GIS Cut Line= 3
     2387720.114      401903.989     2387853.044      401635.608
     2387846.251      401594.674
#Sta/Elev= 30
       0     410      24  405.64    79.9  390.71   115.8  386.34   119.8  385.88
   131.8  385.65   155.7  384.33   159.7  383.67   163.7  383.59   171.7  384.82
   175.7  385.02   195.7  385.32   215.6  385.17   223.6  383.78   227.6  382.91
   231.6  382.77   235.6  382.89   239.6   383.7   243.6  386.14   247.6  387.93
   259.6     389  265.32390.3376   271.5  392.34   275.5  393.04   283.5  393.62
  299.16 393.942   303.3  395.78     307  399.19   310.8   401.9     341     420
#Mann= 5 ,-1 , 0
       0     .12       0   223.6    .045       0   239.6     .12       0
  265.32    .016       0  299.16     .12       0
Bank Sta=223.6,239.6
XS Rating Curve= 0 ,0
Exp/Cntr=0.3,0.1

Type RM Length L Ch R = 1 ,1081.2  ,130.1,129,127.9
XS GIS Cut Line= 3
     2388044.114      401915.499     2388044.843      401623.809
     2388030.733      401580.537
#Sta/Elev= 30
       0     400      28  390.89      40     388      48  386.78    83.9  385.27
    95.9  385.32   111.9  384.28   127.9  384.36   131.9  384.04   143.8  381.88
   155.8  381.47   163.8  380.71   167.8  380.77   171.8  381.57   175.8  382.92
   191.8  385.08   203.8  387.46   215.8  389.22   223.8     391   239.8  392.31
   255.7  395.32   259.7  395.64   267.7  396.22   283.7  395.97   287.7  396.88
   291.7  399.99  294.45401.6111   303.1  405.21     322  414.91   337.2     422
#Mann= 5 ,-1 , 0
       0     .12       0   155.8    .045       0   171.8     .12       0
   259.7    .016       0  294.45     .12       0
#XS Ineff= 2 , 0
           91.01  388.38
Permanent Ineff=
       F       F
Bank Sta=155.8,171.8
XS Rating Curve= 0 ,0
Exp/Cntr=0.3,0.1

Type RM Length L Ch R = 1 ,952.2   ,189.3,190.8,192.2
XS GIS Cut Line= 3
     2388172.114        401898.9     2388159.309      401597.343
      2388140.05      401548.601
#Sta/Elev= 30
       0     400    23.8  390.34   40.63 385.237    47.7  383.99    51.6  383.69
    75.5  383.94    91.3  383.08   101.7   380.9   111.2  380.35   116.7  380.96
   127.1  382.45     135  385.22   150.9   386.8   170.8  387.76   194.6  389.72
   218.4  392.62   230.3  392.69   238.3  394.54   258.1  396.26  265.55397.8217
     278  398.63   293.9  398.13   297.9  399.25  300.07400.7746   301.8  401.99
   305.6   403.8   313.1  406.28   320.6  409.21     343   419.3   354.2     424
#Mann= 6 ,-1 , 0
       0     .12       0   40.63     .08       0   101.7    .045       0
   116.7     .12       0  265.55    .016       0  300.07     .12       0
Bank Sta=101.7,116.7
XS Rating Curve= 0 ,0
Exp/Cntr=0.3,0.1

Type RM Length L Ch R = 1 ,761.4   ,193.4,193.3,193.2
XS GIS Cut Line= 3
     2388329.594      401923.057     2388356.012      401884.435
     2388360.147       401556.57
#Sta/Elev= 30
       0     400    31.2  387.16   44.34384.3532    58.8  382.62    66.8  383.47
    78.8  383.59    94.8  381.67   110.8   383.6   122.8  383.64   126.8   382.7
   131.3  380.36   134.8  379.34   138.8   379.1   146.3  379.67  146.48379.6916
   150.8   380.1   154.8  381.67   158.8  384.86   162.8  386.07   190.8  386.65
   242.7  391.03   298.7   396.4   306.7  397.45   312.7 399.155   322.7  400.62
   338.7  400.89   342.7  403.55  347.21407.8562   350.7  410.02   374.7     420
#Mann= 7 ,-1 , 0
       0     .12       0   44.34     .08       0   131.3    .045       0
   146.3     .08       0  146.48     .12       0   312.7    .016       0
  347.21     .12       0
#XS Ineff= 2 , 0
          115.09  385.75
Permanent Ineff=
       F       F
Bank Sta=131.3,146.3
XS Rating Curve= 0 ,0
Exp/Cntr=0.3,0.1

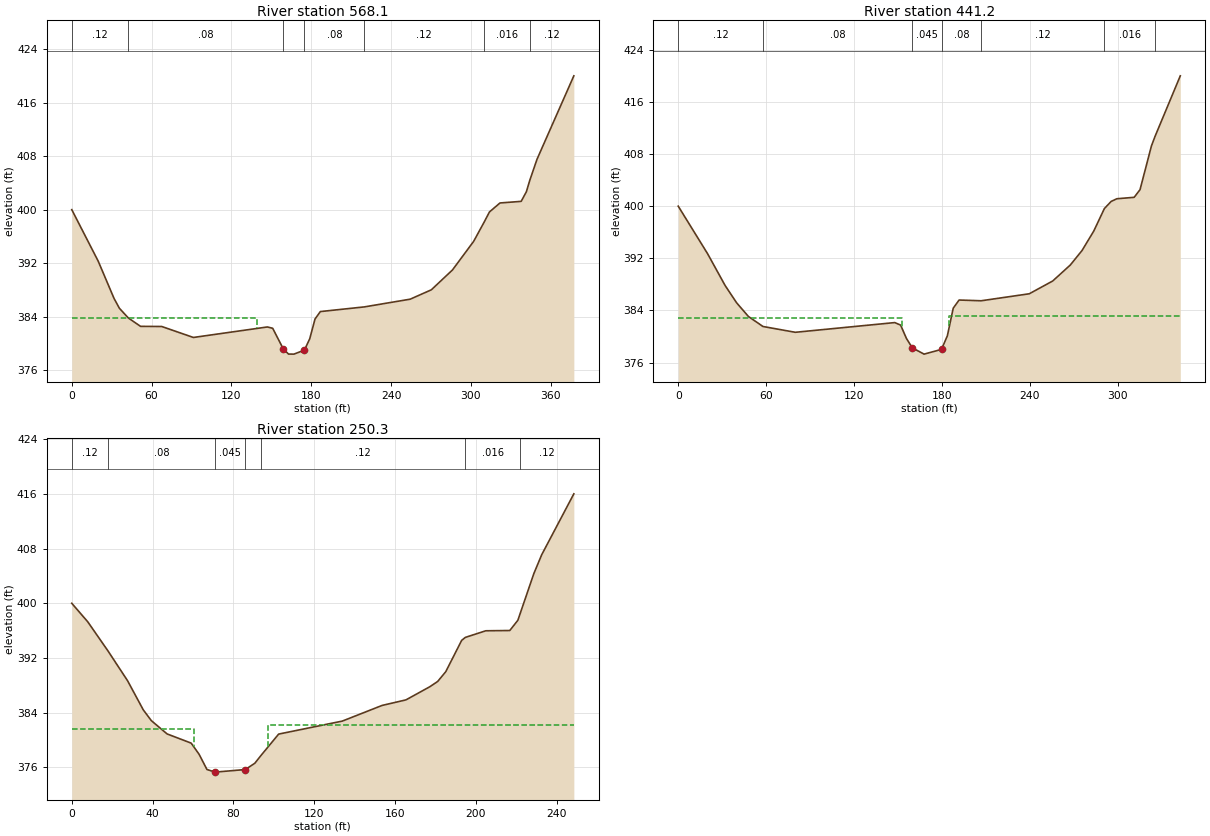
Type RM Length L Ch R = 1 ,568.1   ,125.7,126.9,128.2
XS GIS Cut Line= 3
     2388548.114      401958.606     2388551.436      401644.711
     2388564.114      401582.587
#Sta/Elev= 30
       0     400    19.9  392.29    31.8  386.72    35.8  385.26   42.52383.8112
    51.7  382.56    67.6  382.54    91.4   380.9     147  382.47     151  382.27
     159  379.17   162.9  378.42   166.9  378.41   174.8     379   178.8  380.69
   182.8  383.66   186.8  384.77  219.82385.4663   254.3  386.62   270.2  388.02
   286.1  390.99     302  395.26  309.94398.1552   313.9  399.66   321.8     401
   337.7  401.24   341.6  402.66  344.15404.3557   349.6  407.52   377.3     420
#Mann= 7 ,-1 , 0
       0     .12       0   42.52     .08       0     159    .045       0
   174.8     .08       0  219.82     .12       0  309.94    .016       0
  344.15     .12       0
#XS Ineff= 2 , 0
          139.51  383.75
Permanent Ineff=
       F       F
Bank Sta=159,174.8
XS Rating Curve= 0 ,0
Exp/Cntr=0.3,0.1

Type RM Length L Ch R = 1 ,441.2   ,195.3,190.9,186.4
XS GIS Cut Line= 3
     2388664.868      401959.783     2388684.446      401668.869
     2388701.183      401620.537
#Sta/Elev= 30
       0     400      20  392.72      32  387.83    39.9  385.16    47.9  383.08
   57.83381.5408    79.9  380.65   147.8  382.14   151.8  381.75   155.8  379.69
   159.8  378.26   167.8   377.3   179.7  378.03   183.7  380.11   187.7  384.35
   191.7   385.6  206.77385.4863   239.6  386.56   255.6  388.52   267.6  390.97
   275.6  393.19   283.6  396.17  290.88399.6354   295.5  400.73   299.4  401.14
   311.2  401.36   315.2  402.53     323  409.25  325.55410.7609   342.7     420
#Mann= 7 ,-1 , 0
       0     .12       0   57.83     .08       0   159.8    .045       0
   179.7     .08       0  206.77     .12       0  290.88    .016       0
  325.55     .12       0
#XS Ineff= 2 , 0
          152.43  382.85  185.05          383.13
Permanent Ineff=
       F       F
Bank Sta=159.8,179.7
XS Rating Curve= 0 ,0
Exp/Cntr=0.3,0.1

Type RM Length L Ch R = 1 ,250.3   ,229,250.3,271.5
XS GIS Cut Line= 3
     2388876.114      401882.265     2388852.114      401698.752
     2388864.175      401636.477
#Sta/Elev= 30
       0     400     7.9   397.3   17.99393.0078    27.6  388.69    35.4  384.42
    39.4  382.84    47.2   380.9    59.1  379.56      63  377.94    66.9  375.71
    70.9  375.32    85.9   375.7    90.6  376.62   93.74377.7874   102.4  380.88
   133.9  382.78   153.6  385.07   165.4  385.88   177.2   387.8   181.1  388.57
   185.1     390     193  394.59  194.84395.0178   204.9  395.98   216.8  396.02
   220.8  397.52  222.05398.6033   228.7  404.34   232.6   407.1   248.5     416
#Mann= 7 ,-1 , 0
       0     .12       0   17.99     .08       0    70.9    .045       0
    85.9     .08       0   93.74     .12       0  194.84    .016       0
  222.05     .12       0
#XS Ineff= 2 , 0
           60.34  381.62   96.95          382.25
Permanent Ineff=
       F       F
Bank Sta=70.9,85.9
XS Rating Curve= 0 ,0
Exp/Cntr=0.3,0.1

Chan Stop Cuts=-1
Use User Specified Reach Order=0
Composite Channel Slope=5